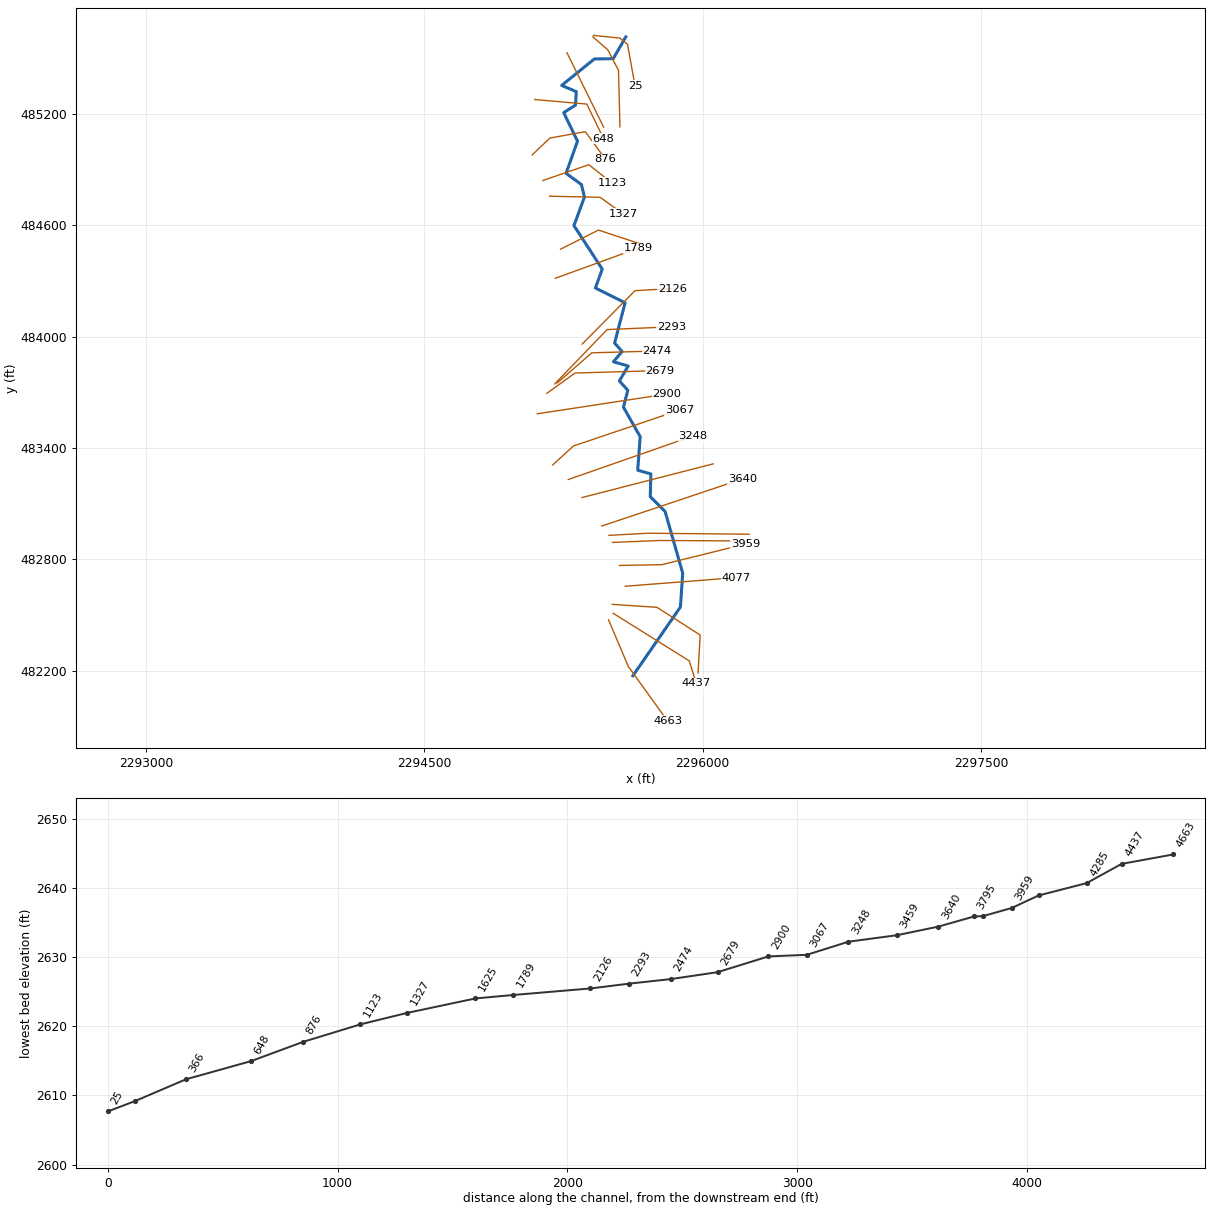
--- SHOCKRNT1.prj (project) ---

Proj Title=SHOCKRNT1
Current Plan=p01
Default Exp/Contr=0,0
English Units
Geom File=g01
Flow File=f01
Plan File=p01
BEGIN DESCRIPTION:
----------MODEL BY WOOD PLC 2021----------
Stream Name: Shock Run Tributary 1
Flood Zone: Approximate
Pocahontas County, WV
HEC-RAS Version: RAS 6.1
Vertical Datum: NAVD88
Projection: NAD 1983 StatePlane West Virginia S FIPS 4702 (US Feet)
Terrain: 1-meter LIDAR (FEMA Region III 3DEP collected 2016-2018)
Land Use: 2019 NLCD
Hydrologic Method:
WV SIR2010-5033 regression equations
Model Notes:
END DESCRIPTION:
DSS Export Rating Curves= 0
DSS Export Rating Curve Sorted= 0
DSS Export Volume Flow Curves= 0
DXF OffsetX= 0
DXF OffsetY= 0
DXF ScaleX= 0
DXF ScaleY= 0

--- SHOCKRNT1.p01 (plan) ---

Plan Title=Floodplain
Program Version=6.10
Short Identifier=Floodplain
Geom File=g01
Flow File=f01
Subcritical Flow
K Sum by GR= 0
Std Step Tol= 0.01
Critical Tol= 0.01
Num of Std Step Trials= 20
Max Error Tol= 0.3
Flow Tol Ratio= 0.001
Split Flow NTrial= 30
Split Flow Tol= 0.02
Split Flow Ratio= 0.02
Log Output Level= 0
Friction Slope Method= 1
Unsteady Friction Slope Method= 2
Unsteady Bridges Friction Slope Method= 1
Parabolic Critical Depth
Global Vel Dist= 0 , 0 , 0
Global Log Level= 0
CheckData=True
Encroach Param=-1 ,0,0, 0
Mapping Interval=1HOUR
Computation Time Step Use Courant=        0
Computation Time Step Use Time Series=    0
Computation Time Step Count To Double=0
Computation Time Step Max Doubling=0
Computation Time Step Max Halving=0
Computation Time Step Residence Courant=0
Run HTab= 0
Run UNet= 0
Run Sediment= 0
Run PostProcess= 0
Run WQNet= 0
Run RASMapper=-1
UNET Theta= 0
UNET Theta Warmup= 0
UNET ZTol= 0
UNET ZSATol= 0
UNET MxIter= 0
UNET Max Iter WO Improvement= 0
UNET MaxInSteps= 0
UNET DtIC= 0
UNET DtMin= 0
UNET MaxCRTS= 0
UNET WFStab= 0
UNET SFStab= 0
UNET WFX= 1
UNET SFX= 1
UNET Gravity=32.174
UNET 1D Methodology=Finite Difference
UNET DSS MLevel= 1
UNET Pardiso=0
UNET DZMax Abort= 0
UNET Use Existing IB Tables= 0
UNET Froude Reduction=False
UNET Froude Limit= 0
UNET Froude Power= 0
UNET D1 Cores= 0
UNET WindReference=Eulerian
UNET WindDragFormulation=Hsu (1988)
UNET D2 Coriolis=0
UNET D2 Cores= 0
UNET D2 Theta= 1
UNET D2 Theta Warmup= 1
UNET D2 Z Tol= 0.01
UNET D2 Volume Tol= 0.01
UNET D2 Max Iterations= 20
UNET D2 Equation= 0
UNET D2 RampUpFraction=0.1
UNET D2 TimeSlices= 1
UNET D2 Turbulence Formulation=Non-Conservative (original)
UNET D2 Eddy Viscosity=0.3
UNET D2 Transverse Eddy Viscosity=0.1
UNET D2 Smagorinsky Mixing=0
UNET D2 BCVolumeCheck=0
UNET D2 Cores=0
UNET D2 SolverType=PARDISO (Direct)
UNET D2 Minimum Iterations= 2147483647
UNET D2 Maximum Iterations= 2147483647
UNET D2 Restart Number= 10
UNET D2 Relaxation Coeff=1.3
UNET D2 SOR Precondition Iterations= 10
UNET D2 ILUT Maximum Fill= 8
UNET D2 ILUT Tolerance=1E-08
UNET D1D2 MaxIter= 0
UNET D1D2 ZTol=0.01
UNET D1D2 QTol=0.1
UNET D1D2 MinQTol=1
Write IC File= 0
Write IC File at Fixed DateTime=0
Write IC File at Sim End=0
Echo Input=False
Echo Parameters=False
Echo Output=False
Write Detailed= 0
HDF Write Warmup=0
HDF Write Time Slices=0
HDF Flush=0
HDF Compression= 1
HDF Chunk Size= 1
HDF Spatial Parts= 1
HDF Use Max Rows=0
HDF Fixed Rows= 1
Calibration Method= 0
Calibration Iterations= 20
Calibration Max Change=0.05
Calibration Tolerance=0.2
Calibration Maximum=1.5
Calibration Minimum=0.5
Calibration Optimization Method= 1
WQ AD Non Conservative
WQ ULTIMATE=-1
WQ Max Comp Step=1HOUR
WQ Output Interval=15MIN
WQ Output Selected Increments= 0
WQ Output face flow=0
WQ Output face velocity=0
WQ Output face area=0
WQ Output face dispersion=0
WQ Output cell volume=0
WQ Output cell surface area=0
WQ Output cell continuity=0
WQ Output cumulative cell continuity=0
WQ Output face conc=0
WQ Output face dconc_dx=0
WQ Output face courant=0
WQ Output face peclet=0
WQ Output face adv mass=0
WQ Output face disp mass=0
WQ Output cell mass=0
WQ Output cell source sink temp=0
WQ Output nsm pathways=0
WQ Output nsm derived pathways=0
WQ Create Restart=0
WQ Fixed Restart=0
WQ System Summary=0
WQ Write To DSS=0
Sorting and Armoring Iterations= 10
XS Update Threshold= 0.02
Bed Roughness Predictor= 0
Hydraulics Update Threshold= 0.02
Energy Slope Method= 1
Volume Change Method= 1
Sediment Retention Method= 0
Sediment TS Multiplier= 1
Warm Up Method= 0
XS Weighting Method= 0
Number of US Weighted Cross Sections= 1
Number of DS Weighted Cross Sections= 1
Upstream XS Weight=0
Main XS Weight=1
Downstream XS Weight=0
Number of DS XS's Weighted with US Boundary= 1
Upstream Boundary Weight= 1
Weight of XSs Associated with US Boundary= 0
Number of US XS's Weighted with DS Boundary= 1
Downstream Boundary Weight= 0.5
Weight of XSs Associated with DS Boundary= 0.5
Percentile Method= 0
Sediment Output Level= 3
Mass or Volume Output= 0
Output Increment Type= 1
Profile and TS Output Increment= 1
Transport Output Increment 1
XS Output Flag= 0
XS Output Increment= 10
Read HDF5 Sediment Hotstart= 0
Sediment Hotstart Type= 0
Write Gradation File= 0
Read Gradation Hotstart= 0
Write HDF5 File= 1
Write Binary Output= 1
Write DSS Sediment File= 0
DSS Sediment Output Type= 1
SV Curve= 0
Specific Gage Flag= 0
Subcell Erosion Methods= 0
Subcell Deposition Methods= 0
Advection Scheme= 1
Matrix Solver= 0
Implicit Weighting Factor= 1
Maximum Outer Loop Convergence Iterations= 5
Convergence Maximum Absolute= 0.001
Convergence RMSE= 0.0001
Grain Fractions Max Abs Error= 0.001
Max Subgrid Regions= 1
Max Subgrid Length Scale= 3.402823E+38
Initial Layer Thickness= 3.402823E+38
Min Layer Thickness= 3.402823E+38
Max Layer Thickness= 3.402823E+38
Number of Layers= 5

--- SHOCKRNT1.f01 (steady flow) ---

Flow Title=Flow
Program Version=6.00
Number of Profiles= 6
Profile Names=01pct,10pct,04pct,02pct,0_2pct,01plus
River Rch & RM=SHOCKRNT1,Main            ,4663
     689     366     486     584     958    1020
Boundary for River Rch & Prof#=SHOCKRNT1,Main            , 1
Up Type= 0
Dn Type= 3
Dn Slope=0.01225
Boundary for River Rch & Prof#=SHOCKRNT1,Main            , 2
Up Type= 0
Dn Type= 3
Dn Slope=0.01225
Boundary for River Rch & Prof#=SHOCKRNT1,Main            , 3
Up Type= 0
Dn Type= 3
Dn Slope=0.01225
Boundary for River Rch & Prof#=SHOCKRNT1,Main            , 4
Up Type= 0
Dn Type= 3
Dn Slope=0.01225
Boundary for River Rch & Prof#=SHOCKRNT1,Main            , 5
Up Type= 0
Dn Type= 3
Dn Slope=0.01225
Boundary for River Rch & Prof#=SHOCKRNT1,Main            , 6
Up Type= 0
Dn Type= 3
Dn Slope=0.01225
DSS Import GetInterval= 0
DSS Import GetPeak= 0
DSS Import FillOption= 0

--- SHOCKRNT1.g01 (geometry) ---

Geom Title=Geometry
Program Version=6.10

River Reach=SHOCKRNT1       ,Main
Reach XY= 30
2295624.60715197482172.1331588032295880.90913281482542.765947729
2295893.12203489482725.2531155652295798.15568939483057.553960145
2295718.27297513483137.5790625662295721.50295556483259.897059396
2295650.59102389 483280.017097892295663.91908123483460.513127983
2295573.69813305483619.7270483972295597.19185247483710.340056136
2295551.72114289483761.2789306492295599.42609997483841.621945813
2295519.73990764483864.2400108132295566.57938088483919.603745222
2295525.86391114483965.3369214832295582.75585772 484182.03104189
2295422.59410456484261.7539795642295459.44901772484363.753119394
2295307.01198664 484598.170957642295363.39704446484751.424916223
2295347.71400496484818.9739937342295264.45695363484880.040144563
2295326.15007173485053.3039056512295251.76898688 485207.03391315
2295315.42437139485247.5121786452295319.56609538485320.120957315
2295240.88285381485353.5851292312295416.67613739485495.982154146
2295518.89903006485497.8899587242295586.31785847485615.276863053

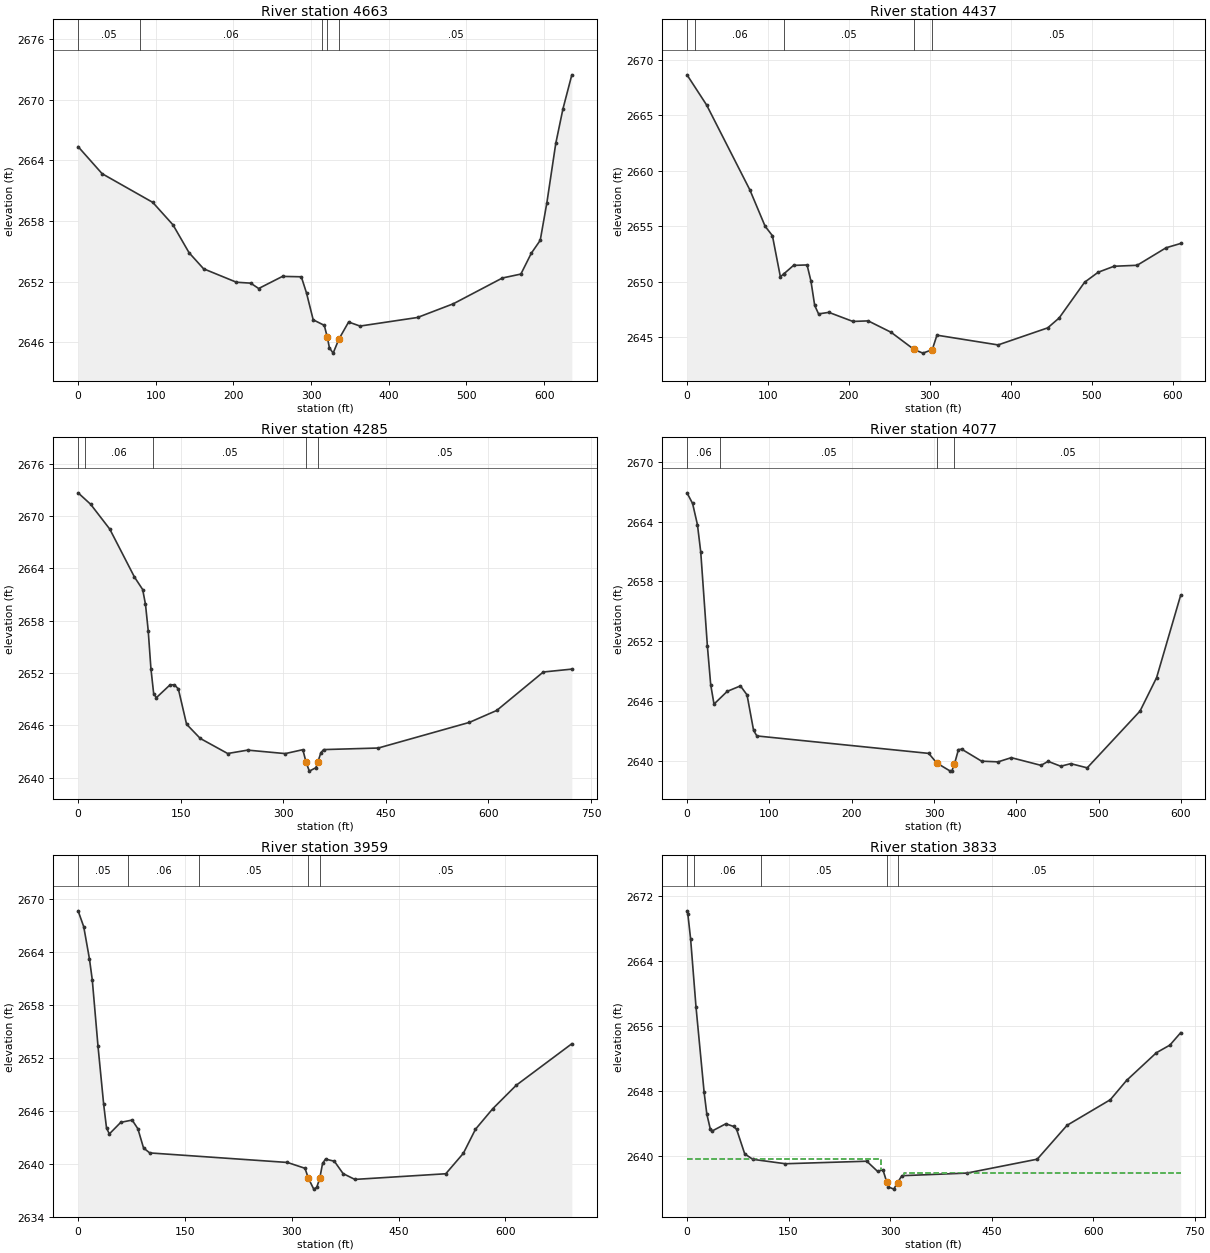
Type RM Length L Ch R = 1 ,4663    ,225.8,225.8,225.8
XS GIS Cut Line= 3
2295493.30018649 482473.641777082295600.49116119482221.253697832
2295811.81833205481927.963950661
#Sta/Elev= 30
       0 2665.36    30.9 2662.68    96.1 2659.84   122.2 2657.61   142.9 2654.85
   161.6 2653.26   203.9 2651.93   222.2 2651.84   232.5 2651.31   263.2 2652.51
   287.4 2652.47   294.1 2650.86   302.7 2648.21     317 2647.66   320.82646.501
   323.6 2645.43   328.4 2644.91   335.82646.301   348.3 2647.99     363 2647.59
     437 2648.44   483.2  2649.8   546.3 2652.35   570.1 2652.74   583.5  2654.8
     595 2656.08   603.6 2659.82     615 2665.67   624.3 2669.11   635.7 2672.47
#Mann= 5 ,-1,0
       0     .05       0      80     .06       0  314.21     .05       0
   320.8    .045       0   335.8     .05       0
Bank Sta=320.8,335.8
XS Rating Curve= 0 ,0
Exp/Cntr=0.3,0.1

Type RM Length L Ch R = 1 ,4437    ,152.3,152.3,152.3
XS GIS Cut Line= 3
2295518.38450864482508.7545656272295928.15008452482252.651080702
2295966.34857041482131.978591195
#Sta/Elev= 30
       0 2668.66    24.2 2665.94    77.6 2658.28    96.5 2654.99   105.5 2654.14
   115.3 2650.44     120 2650.71     120 2650.72   131.6 2651.46   148.3  2651.5
   153.1 2650.04   157.7 2647.85   162.5 2647.08   175.2 2647.22   204.9  2646.4
   223.8 2646.45   252.1 2645.42   280.4 2643.87   291.3 2643.54   302.9 2643.85
   308.7 2645.16   384.2 2644.28   445.5 2645.82   459.6 2646.71   491.1 2649.94
   507.8 2650.84   527.4 2651.38     556 2651.47   591.7 2653.05   609.8 2653.44
#Mann= 5 ,-1,0
       0     .05       0      10     .06       0     120     .05       0
   280.4    .045       0   302.9     .05       0
Bank Sta=280.4,302.9
XS Rating Curve= 0 ,0
Exp/Cntr(USF)=0,0
Exp/Cntr=0.3,0.1

Type RM Length L Ch R = 1 ,4285    ,198.9,208.4,217.9
XS GIS Cut Line= 4
2295513.93816285482556.8754586242295754.52060321482540.876019668
2295987.18410816482391.5546657462295975.89819188482187.540025213
#Sta/Elev= 30
       0 2672.67    18.3 2671.36    46.3 2668.51    82.4 2663.01    94.4 2661.58
    98.5 2659.89   102.5 2656.87   106.5 2652.49   110.5 2649.63   114.5 2649.18
   134.5 2650.65   140.9 2650.65   146.6 2650.17   158.6 2646.13   178.6  2644.5
   218.7 2642.77   247.9 2643.16   302.9 2642.76   328.6 2643.21   333.4 2641.75
   338.1 2640.75   347.6 2641.14   350.52641.785     355 2642.87     359 2643.22
   438.9  2643.4   572.1 2646.34   612.1 2647.71   680.2 2652.12   721.9 2652.45
#Mann= 5 ,-1,0
       0     .05       0      10     .06       0     110     .05       0
   333.4    .045       0   350.5     .05       0
Bank Sta=333.4,350.5
XS Rating Curve= 0 ,0
Exp/Cntr=0.3,0.1

Type RM Length L Ch R = 1 ,4077    ,115.5,117.7,120.1
XS GIS Cut Line= 2
2295583.49556413482654.6033299232296181.44324663482701.019264456
#Sta/Elev= 30
       0 2666.89     6.8 2665.82    12.7 2663.69    16.7 2660.95    24.8 2651.49
    28.8 2647.64    32.8 2645.69    48.8 2646.97    64.9 2647.52    72.9 2646.62
    80.9 2643.05    84.9  2642.5   293.6 2640.75303.40472639.786   319.8 2638.97
   321.6 2638.97324.86792639.686   329.7 2641.13   333.7 2641.17   357.8 2639.97
   377.8  2639.9   393.9 2640.32     430 2639.55   438.6 2639.95     454 2639.46
   466.1 2639.72   486.1  2639.3   550.3    2645   570.4 2648.35   599.7 2656.64
#Mann= 4 ,-1,0
       0     .06       0      40     .05       0303.4047    .045       0
324.8679     .05       0
Bank Sta=303.4047,324.8679
XS Rating Curve= 0 ,0
Exp/Cntr(USF)=0,0
Exp/Cntr=0.3,0.1

Type RM Length L Ch R = 1 ,3959    ,126.7,125.3,120.4
BEGIN DESCRIPTION:
structure xs 4
END DESCRIPTION:
XS GIS Cut Line= 3
2295552.24225749482766.5943453652295781.43317282482770.935082397
 2296232.0016768482882.057950433
#Sta/Elev= 30
       0 2668.66     7.9 2666.86    15.9 2663.23    19.9 2660.85    27.9 2653.37
    35.9 2646.75    39.9 2644.07    43.9  2643.4    59.9 2644.71    75.9 2644.97
    83.9 2643.99    91.9 2641.81   100.6 2641.25   293.9 2640.17   318.6 2639.51
   323.32638.391   330.9 2637.15   335.1 2637.35   339.3 2638.37   343.3 2640.06
   347.4 2640.55   359.8 2640.31   372.1 2638.91   388.6 2638.25   516.3 2638.89
     541 2641.21     558 2643.93   582.2 2646.25   615.2 2648.91   693.3 2653.61
#Mann= 5 ,-1,0
       0     .05       0      70     .06       0     170     .05       0
   323.3    .045       0   339.3     .05       0
Bank Sta=323.3,339.3
XS Rating Curve= 0 ,0
Exp/Cntr(USF)=0,0
Exp/Cntr=0.5,0.3

Type RM Length L Ch R = 1 ,3833    ,39.6,38.8,38.8
BEGIN DESCRIPTION:
structure xs 3
END DESCRIPTION:
XS GIS Cut Line= 3
2295514.91191901482890.7394244982295767.54281431482901.157193376
2296244.15574049482898.552751157
#Sta/Elev= 30
       0 2670.17     1.3 2669.73     5.3 2666.76    13.3 2658.36    25.3 2647.87
    29.3 2645.19    34.3  2643.4    37.3 2643.12    57.4    2644    68.9 2643.67
    73.3 2643.32    85.3  2640.3    97.3 2639.63   145.4 2639.09   265.6  2639.4
   281.5 2638.16   289.5 2638.35   295.22636.816   297.7 2636.24   305.5 2635.97
   311.12636.775   317.5 2637.62   413.5 2637.94   517.5 2639.65   561.5 2643.81
   625.5 2646.96   649.5 2649.33   693.5 2652.73   713.5 2653.67   729.5  2655.2
#Mann= 5 ,-1,0
       0     .07       0      10     .06       0     110     .05       0
   295.2    .045       0   311.1     .05       0
#XS Ineff= 2 , 0
           286.4 2639.66   319.9         2637.98
Permanent Ineff=
       F       F
Bank Sta=295.2,311.1
XS Rating Curve= 0 ,0
Exp/Cntr(USF)=0,0
Exp/Cntr=0.5,0.3

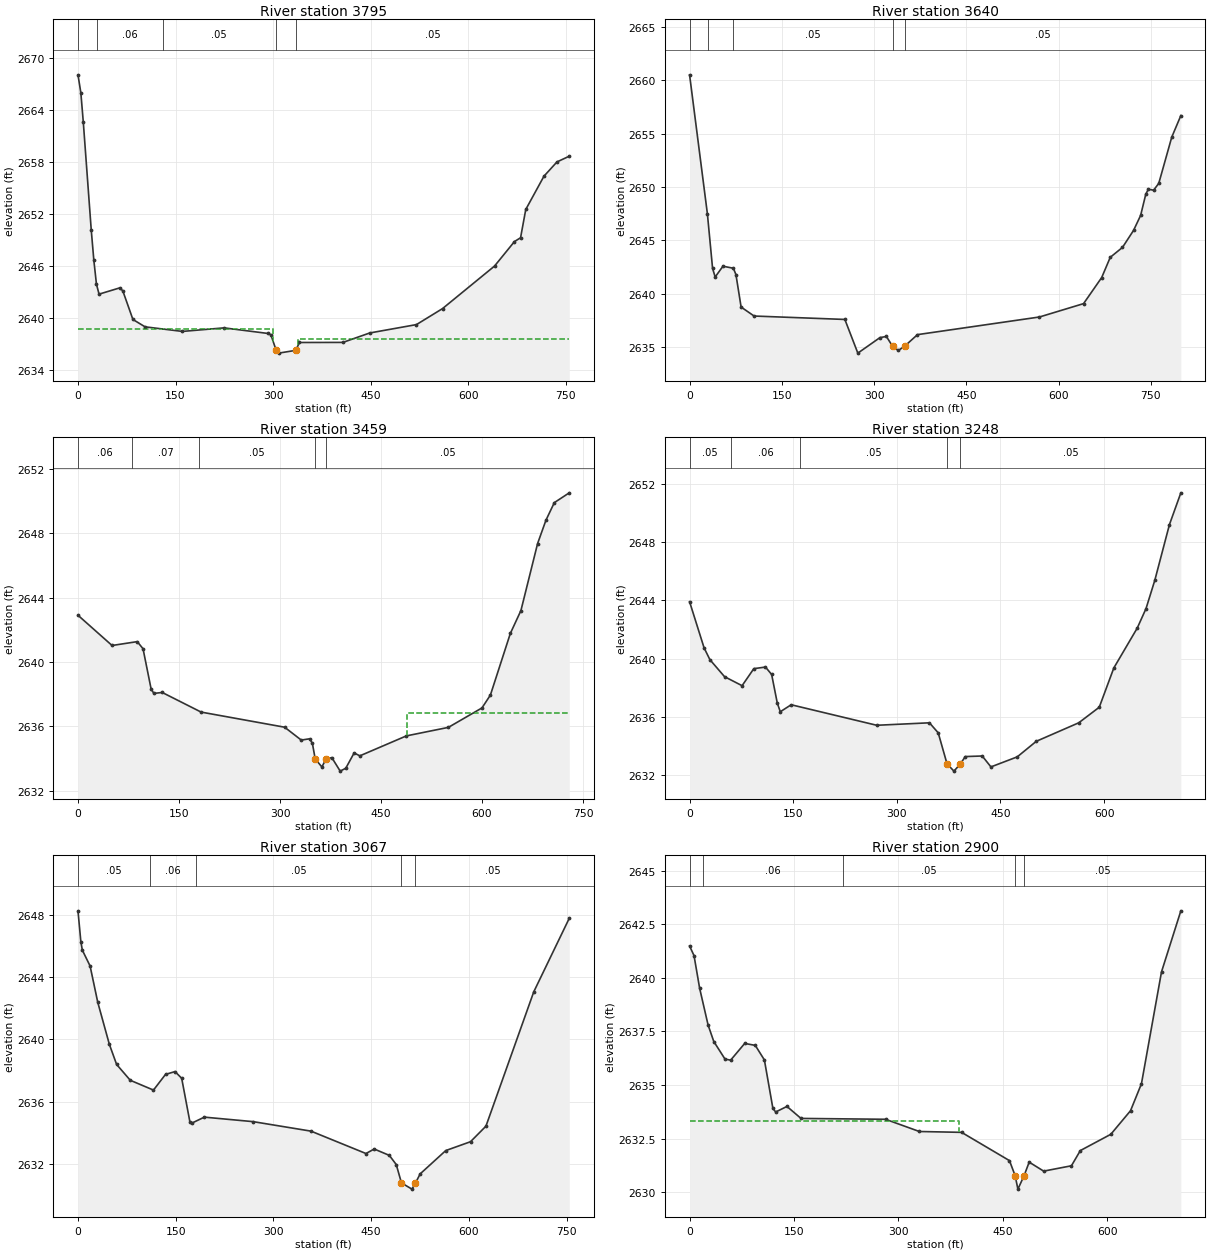
Type RM Length L Ch R = 1 ,3795    ,149.5,154.5,161.3
BEGIN DESCRIPTION:
structure xs 2
END DESCRIPTION:
XS GIS Cut Line= 3
2295495.81267607482928.9379103852295705.90434845 482940.22382667
2296251.10091975482935.014942231
#Sta/Elev= 30
       0  2668.1     4.4 2666.03     8.2 2662.61    20.4 2650.16    24.4 2646.65
    28.4  2643.9    32.4 2642.74    64.5 2643.47      69 2643.11    84.5 2639.81
   103.2 2638.96   160.6 2638.43   224.7 2638.84   292.7 2638.19   296.7 2638.04
   304.7 2636.27   308.7 2635.92   334.8 2636.24   340.7 2637.15   407.5 2637.16
   448.7 2638.25   520.6 2639.22   560.7 2641.07   640.7 2645.99   671.3 2648.82
   680.7 2649.26   688.7 2652.53   716.7 2656.38   736.7 2658.03   755.6 2658.69
#Mann= 5 ,-1,0
       0     .07       0      30     .06       0     130     .05       0
   304.7    .045       0   334.8     .05       0
#XS Ineff= 2 , 0
           300.7  2638.7   338.8          2637.5
Permanent Ineff=
       F       F
Bank Sta=304.7,334.8
XS Rating Curve= 0 ,0
Exp/Cntr(USF)=0,0
Exp/Cntr=0.5,0.3

Type RM Length L Ch R = 1 ,3640    ,177.4,180.6,177.5
XS GIS Cut Line= 2
2295456.70295175482978.9620472872296214.20441037483232.480242944
#Sta/Elev= 30
       0 2660.49      29 2647.48    37.4 2642.39    41.6 2641.58    54.3 2642.59
    71.2  2642.4    75.4 2641.81    83.8 2638.77   104.9 2637.93   252.5 2637.61
   273.6 2634.46   309.5 2635.91     320 2636.02     330 2635.11   339.5 2634.71
   349.5  2635.1   370.6 2636.19   568.9 2637.84   640.6 2639.09   670.1 2641.53
     684 2643.42   703.9 2644.35   721.9 2645.94   733.4 2647.34   741.8 2649.33
     746 2649.79   754.5  2649.7   762.9 2650.34     784 2654.66   798.8 2656.68
#Mann= 5 ,-1,0
       0     .07       0      30     .06       0      70     .05       0
     330    .045       0   349.5     .05       0
Bank Sta=330,349.5
XS Rating Curve= 0 ,0
Exp/Cntr=0.3,0.1

Type RM Length L Ch R = 1 ,3459    ,188.4,211,206.4
XS GIS Cut Line= 2
2295350.98640841483132.7738602212296057.70180469483314.199305237
#Sta/Elev= 30
       0  2642.9    50.6 2641.02      88 2641.26    96.6 2640.82   108.6 2638.32
   112.7 2638.04   125.1  2638.1   182.9 2636.88   306.9 2635.94   331.6 2635.14
     344 2635.22   348.1 2634.94   352.3 2633.97   362.2 2633.47   368.42633.958
     377 2634.05   389.4 2633.21   397.7 2633.39   410.1 2634.34   418.6 2634.16
   487.7  2635.4   550.1 2635.93     600 2637.14   612.5 2637.94   642.1 2641.77
   657.8 2643.19   682.6 2647.36     695 2648.81   707.4  2649.9   729.6 2650.51
#Mann= 5 ,-1,0
       0     .06       0      80     .07       0     180     .05       0
   352.3    .045       0   368.4     .05       0
#XS Ineff= 2 , 0
                          488.56          2636.8
Permanent Ineff=
       F       F
Bank Sta=352.3,368.4
XS Rating Curve= 0 ,0
Exp/Cntr(USF)=0,0
Exp/Cntr=0.3,0.1

Type RM Length L Ch R = 1 ,3248    ,181,181.4,180.4
XS GIS Cut Line= 2
2295276.38939559483229.661040006 2295947.7567233483464.060839768
#Sta/Elev= 30
       0 2643.91      21 2640.74    29.4 2639.93    50.6 2638.76      76 2638.14
      93 2639.31   109.9 2639.42   118.8 2638.91   126.9 2636.96   131.3 2636.35
   147.1 2636.83   270.9 2635.42   347.2 2635.59   359.9  2634.9   372.6 2632.78
   382.6 2632.27     392 2632.76     399 2633.27   423.6 2633.31   436.2 2632.56
   474.3 2633.25   501.9 2634.32   563.3 2635.59     593 2636.66   614.1 2639.36
     648  2642.1   660.7 2643.44   673.4 2645.38   694.6 2649.21   711.1 2651.39
#Mann= 5 ,-1,0
       0     .05       0      60     .06       0     160     .05       0
   372.6    .045       0     392     .05       0
Bank Sta=372.6,392
XS Rating Curve= 0 ,0
Exp/Cntr(USF)=0,0
Exp/Cntr=0.3,0.1

Type RM Length L Ch R = 1 ,3067    ,167.3,167,162.3
XS GIS Cut Line= 3
2295192.91702245483308.6634186082295304.40677744483410.527444536
2295875.80958575483603.639939955
#Sta/Elev= 30
       0 2648.27     4.4 2646.29     6.7 2645.74    18.6 2644.72    30.4 2642.38
    48.2 2639.68    59.3 2638.39    80.3 2637.37   115.9 2636.74   134.4 2637.75
     149 2637.93   159.2  2637.5   171.8  2634.7     175 2634.62     194    2635
     269 2634.71   357.7  2634.1   442.1 2632.66   454.8 2632.95     478 2632.54
   488.6 2631.95   496.6 2630.77   512.7 2630.37   518.1 2630.76   525.3 2631.35
   564.6 2632.85   602.6 2633.42   626.3 2634.42   699.7 2643.06   754.2 2647.79
#Mann= 5 ,-1,0
       0     .05       0     110     .06       0  181.02     .05       0
   496.6    .045       0   518.1     .05       0
Bank Sta=496.6,518.1
XS Rating Curve= 0 ,0
Exp/Cntr(USF)=0,0
Exp/Cntr=0.3,0.1

Type RM Length L Ch R = 1 ,2900    ,216.9,220.9,216.9
XS GIS Cut Line= 2
2295109.85494364483583.9832963592295807.58501426483690.244538918
#Sta/Elev= 30
       0 2641.49     6.4 2641.04    14.5 2639.51    26.6  2637.8    34.8 2637.03
    50.9 2636.21      59 2636.16    79.2 2636.94    94.4 2636.85   107.5 2636.17
   119.7 2633.91   123.7 2633.74   139.9    2634   160.1 2633.44   281.5  2633.4
   330.1 2632.83   390.8 2632.79   459.6 2631.47   467.7 2630.77   471.7 2630.14
   480.6 2630.77   487.9  2631.4   508.7 2630.98   548.6 2631.23   561.4 2631.94
   605.2  2632.7   633.5  2633.8   649.2 2635.06     678 2640.28   705.8 2643.13
#Mann= 5 ,-1,0
       0     .05       0      20     .06       0     220     .05       0
   467.7    .045       0   480.6     .05       0
#XS Ineff= 2 , 0
          387.61 2633.34
Permanent Ineff=
       F       F
Bank Sta=467.7,480.6
XS Rating Curve= 0 ,0
Exp/Cntr(USF)=0,0
Exp/Cntr=0.3,0.1

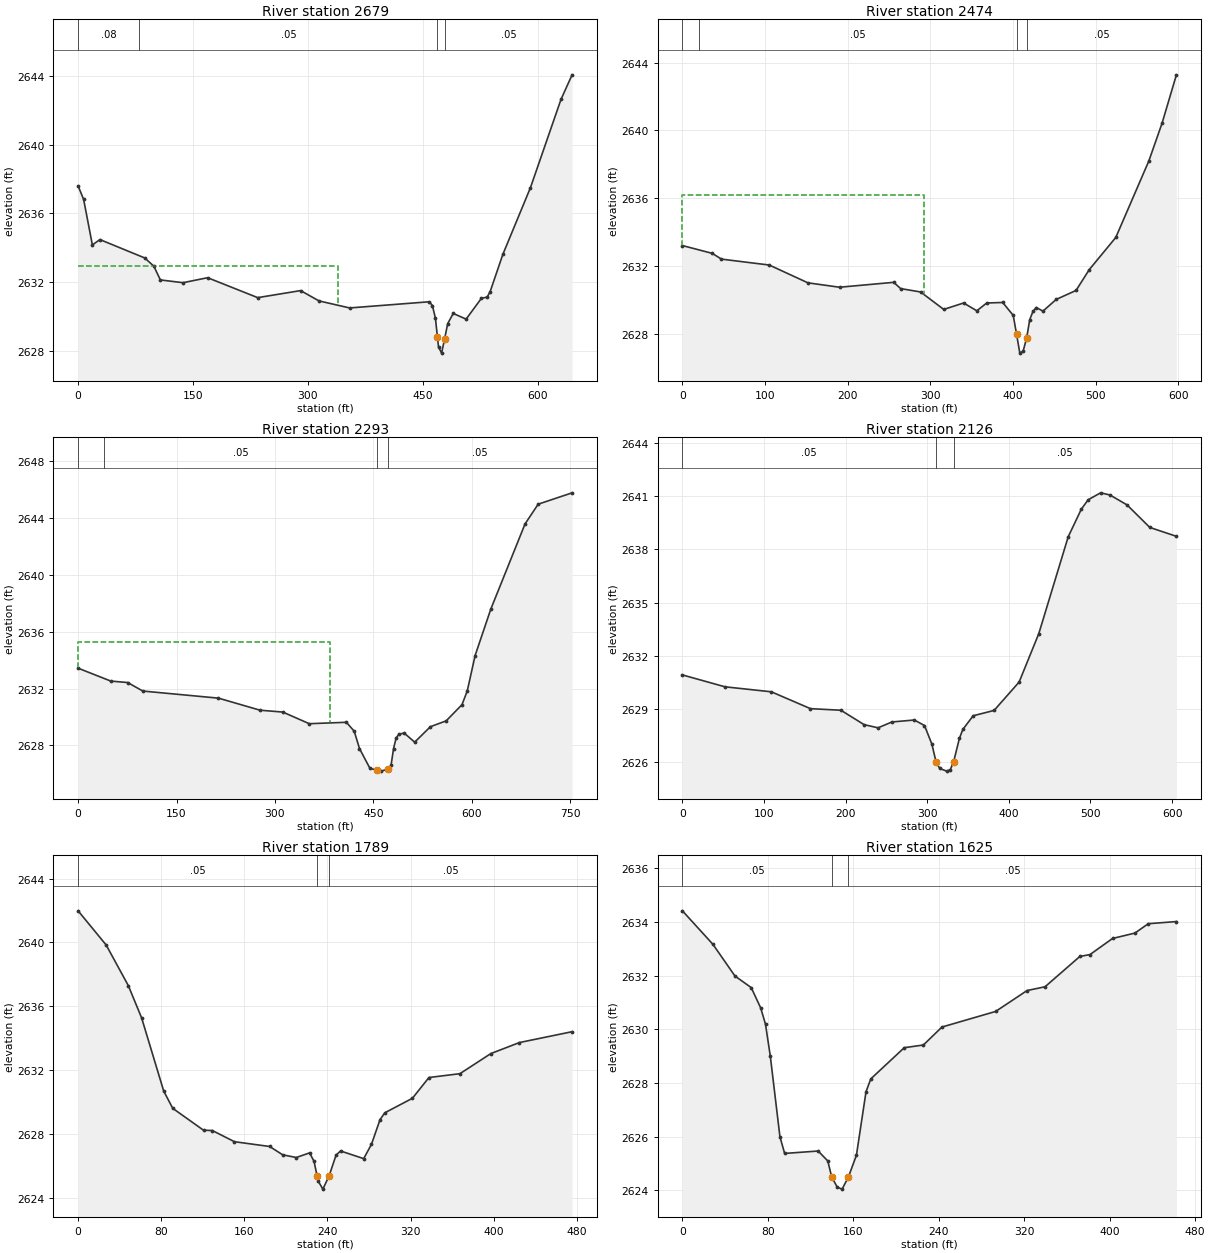
Type RM Length L Ch R = 1 ,2679    ,203,205.2,201.7
XS GIS Cut Line= 3
2295161.07774352483694.253144031 2295312.6562807483803.639717253
 2295770.5172229483816.922372573
#Sta/Elev= 30
       0 2637.59     7.2 2636.81    18.6 2634.16    28.5 2634.47      87  2633.4
    98.9 2632.92   107.4 2632.12     137 2631.96   169.1 2632.25   234.5 2631.09
   290.5  2631.5   314.5  2630.9   354.5 2630.49   458.6 2630.85   462.6 2630.63
   466.6 2629.88   469.2 2628.78   470.6 2628.22   474.6 2627.86   478.6 2628.71
   482.6 2629.58   489.8 2630.17   506.6 2629.84   526.6 2631.05   534.1 2631.12
     538 2631.44   554.6 2633.61   590.6 2637.49   630.6 2642.64     645 2644.06
#Mann= 4 ,-1,0
       0     .08       0      80     .05       0   469.2    .045       0
   478.6     .05       0
#XS Ineff= 2 , 0
          339.94 2632.91
Permanent Ineff=
       F       F
Bank Sta=469.2,478.6
XS Rating Curve= 0 ,0
Exp/Cntr(USF)=0,0
Exp/Cntr=0.3,0.1

Type RM Length L Ch R = 1 ,2474    ,176.1,181.5,172.7
XS GIS Cut Line= 3
2295216.96774602483750.173716933 2295403.2397831483912.543589966
2295753.53011832483922.434140607
#Sta/Elev= 30
       0  2633.2    36.1 2632.74    47.2  2632.4   105.1 2632.05   151.8    2631
     190 2630.74   255.6 2631.03   263.9 2630.66   288.1 2630.46   316.1 2629.43
   340.1 2629.81   356.1 2629.35   368.1 2629.81   387.4 2629.84   400.1 2629.08
   404.2 2627.96   408.1 2626.85   412.1 2626.97   416.42627.748   420.1 2628.83
   424.1 2629.32   428.1 2629.54   436.1 2629.33   452.1 2630.02   476.1 2630.55
   492.1 2631.78   524.2 2633.68   564.2  2638.2   580.2 2640.43   597.5 2643.28
#Mann= 4 ,-1,0
       0     .08       0      20     .05       0   404.2    .045       0
   416.4     .05       0
#XS Ineff= 2 , 0
          292.17  2636.2
Permanent Ineff=
       F       F
Bank Sta=404.2,416.4
XS Rating Curve= 0 ,0
Exp/Cntr(USF)=0,0
Exp/Cntr=0.3,0.1

Type RM Length L Ch R = 1 ,2293    ,152.1,167,176.6
XS GIS Cut Line= 3
2295203.78034517483745.2284416132295485.66103845484037.823898092
 2295831.8303109484052.659724054
#Sta/Elev= 30
       0 2633.44    49.9 2632.53    75.5 2632.43    98.6 2631.83   213.9 2631.33
   277.3 2630.48   311.9 2630.35   352.3 2629.53   408.8 2629.63   420.8    2629
   428.8 2627.78   444.8 2626.38   456.2 2626.25   460.9 2626.19   472.82626.328
   476.9  2626.6   480.7 2627.77   484.6 2628.52   488.9 2628.79   496.9 2628.87
   512.9 2628.23   536.9 2629.32   560.9 2629.73     585 2630.87     593 2631.83
     605 2634.33     629 2637.61   681.1  2643.6   701.1 2644.99   752.8 2645.79
#Mann= 4 ,-1,0
       0     .08       0      40     .05       0   456.2    .045       0
   472.8     .05       0
#XS Ineff= 2 , 0
          383.94 2635.28
Permanent Ineff=
       F       F
Bank Sta=456.2,472.8
XS Rating Curve= 0 ,0
Exp/Cntr(USF)=0,0
Exp/Cntr=0.3,0.1

Type RM Length L Ch R = 1 ,2126    ,339.5,336.8,328.2
XS GIS Cut Line= 3
2295351.61312902483959.860174367 2295636.1971304484247.526312941
2295836.53604833484258.827482671
#Sta/Elev= 30
       0 2630.92    52.2 2630.25   108.9 2629.97   156.9 2629.02   194.2 2628.93
   222.6 2628.12   239.7 2627.94   256.7 2628.27   284.2 2628.38   296.6 2628.07
   305.7 2627.02  310.78 2626.02   315.3 2625.65   323.8  2625.5   328.2 2625.58
   332.3 2626.03   339.5 2627.36   343.6 2627.85   356.3 2628.62   381.9 2628.92
   412.6 2630.52   436.7 2633.25   472.7  2638.7   488.8 2640.26   497.2 2640.79
   512.4 2641.18   523.8 2641.06   544.8  2640.5   572.7 2639.23   605.3 2638.73
#Mann= 3 ,0,0
       0     .05       0  310.78    .045       0   332.3     .05       0
Bank Sta=310.78,332.3
XS Rating Curve= 0 ,0
Exp/Cntr(USF)=0,0
Exp/Cntr=0.3,0.1

Type RM Length L Ch R = 1 ,1789    ,161.2,164.2,164.6
XS GIS Cut Line= 2
2295206.75268067484314.3059522532295653.66257453484476.631844734
#Sta/Elev= 30
       0 2641.98      27 2639.84    48.3  2637.3    61.1 2635.28    82.4 2630.69
    91.1 2629.61   120.7 2628.24   129.2 2628.22   150.5 2627.52   184.4 2627.22
   196.9  2626.7     210 2626.53   222.8 2626.82   227.1 2626.29  230.04 2625.38
   231.3 2625.03   235.6 2624.55  241.65 2625.39   248.3 2626.68   252.6 2626.94
   274.9 2626.46   282.4 2627.36   290.6  2628.9   295.2 2629.33   321.8 2630.24
   337.7 2631.54   367.5 2631.78   397.3 2633.04   424.8 2633.73   475.5 2634.41
#Mann= 3 ,0,0
       0     .05       0  230.04    .045       0  241.65     .05       0
Bank Sta=230.04,241.65
XS Rating Curve= 0 ,0
Exp/Cntr(USF)=0,0
Exp/Cntr=0.3,0.1

Type RM Length L Ch R = 1 ,1625    ,296.6,298,284.5
XS GIS Cut Line= 3
2295234.67124224484471.0553665862295438.91016411484573.960143001
2295661.02807967  484500.9582217
#Sta/Elev= 30
       0 2634.42    28.6 2633.17    49.2 2631.99    64.4 2631.56    73.3  2630.8
    77.8 2630.19    82.3    2629    91.3    2626    95.7 2625.38   127.1 2625.47
   136.1  2625.1   139.72624.511     145 2624.12   149.5 2624.05   155.32624.492
   162.9 2625.31   171.9 2627.68   176.4 2628.16   207.7 2629.32   225.6 2629.42
     243 2630.09   293.2 2630.67   322.7 2631.45   339.5 2631.59   372.1 2632.72
   381.6 2632.79   402.7 2633.39   423.6 2633.59   436.2 2633.94   462.5 2634.02
#Mann= 3 ,-1,0
       0     .05       0   139.7    .045       0   155.3     .05       0
Bank Sta=139.7,155.3
XS Rating Curve= 0 ,0
Exp/Cntr(USF)=0,0
Exp/Cntr=0.3,0.1

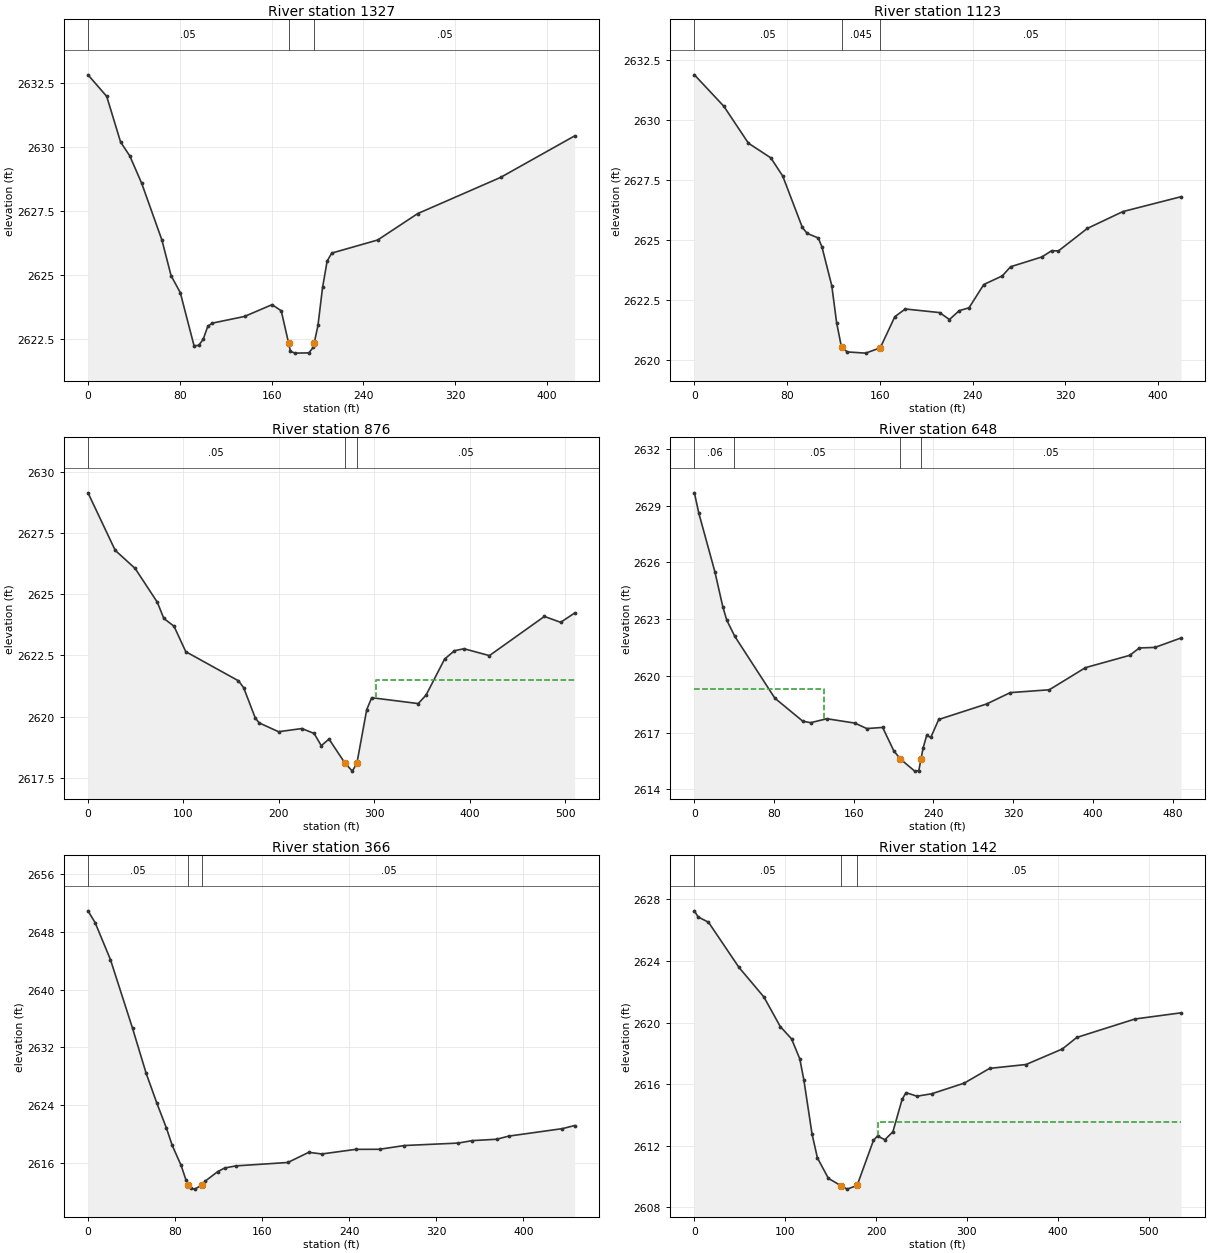
Type RM Length L Ch R = 1 ,1327    ,188.7,203.2,184.4
XS GIS Cut Line= 3
2295175.83014024 484756.579402512295447.84966096484750.791753133
2295571.31951433484662.047796022
#Sta/Elev= 30
       0  2632.8    16.3 2631.96    28.4 2630.18    36.4 2629.64    46.8 2628.57
    64.4 2626.36    72.4 2624.97    80.4 2624.31    92.4 2622.24    96.4 2622.25
   100.4 2622.49   104.4    2623   108.4 2623.12   136.4 2623.38   160.4 2623.84
   168.4  2623.6   174.82622.344   176.4 2622.02   180.4 2621.95   192.4 2621.96
   196.4 2622.18   197.2 2622.36   200.4 2623.03   204.4 2624.51   208.4 2625.54
   212.4 2625.85   252.4 2626.36   287.3 2627.39   359.5  2628.8   424.1 2630.42
#Mann= 3 ,-1,0
       0     .05       0   174.8    .045       0   197.2     .05       0
Bank Sta=174.8,197.2
XS Rating Curve= 0 ,0
Exp/Cntr(USF)=0,0
Exp/Cntr=0.3,0.1

Type RM Length L Ch R = 1 ,1123    ,246.7,247.9,219.8
XS GIS Cut Line= 3
2295140.13963575484841.464926704 2295387.0793425484926.350450898
 2295511.5138041484827.960411491
#Sta/Elev= 30
       0 2631.89    25.4 2630.58    46.6 2629.04    65.9 2628.43    76.2 2627.67
    93.1 2625.53    97.3 2625.28   106.8 2625.09     110 2624.72   118.5  2623.1
   122.7 2621.55   126.9 2620.53     132 2620.34   147.7 2620.29   160.3 2620.51
   172.9 2621.81   181.9 2622.13   211.5 2621.98     220 2621.69   228.4 2622.06
   236.9 2622.18   249.6 2623.15   265.6 2623.51   272.7 2623.89   299.8  2624.3
   308.2 2624.56     314 2624.55     339 2625.49   369.6 2626.19   419.8 2626.81
#Mann= 3 ,-1,0
       0     .05       0   126.9    .045       0   160.3     .05       0
Bank Sta=126.9,160.3
XS Rating Curve= 0 ,0
Exp/Cntr(USF)=0,0
Exp/Cntr=0.3,0.1

Type RM Length L Ch R = 1 ,876     ,227.4,227.7,221.3
XS GIS Cut Line= 4
2295081.97375952 484979.114521052295177.54082284485069.997608111
 2295368.1730212485104.2242084122295476.88436866484955.578080251
#Sta/Elev= 30
       0 2629.14    28.5 2626.79    49.4 2626.05    72.6 2624.67    79.4 2624.01
    90.1 2623.69   102.4 2622.65   157.6 2621.46     163 2621.18   175.2 2619.94
   179.3 2619.74   199.6 2619.38     224 2619.51   236.8 2619.31   244.3 2618.81
   252.4 2619.08   268.7 2618.12   276.8 2617.77   281.6 2618.09   291.9 2620.28
   297.1 2620.77   345.9 2620.53   354.1 2620.88   373.5 2622.35   383.8 2622.69
   393.8 2622.77   420.4 2622.49     478 2624.09     495 2623.85   509.7 2624.23
#Mann= 3 ,-1,0
       0     .05       0   268.7    .045       0   281.6     .05       0
#XS Ineff= 2 , 0
                          301.86         2621.51
Permanent Ineff=
       F       F
Bank Sta=268.7,281.6
XS Rating Curve= 0 ,0
Exp/Cntr(USF)=0,0
Exp/Cntr=0.3,0.1

Type RM Length L Ch R = 1 ,648     ,286.7,282,270.8
XS GIS Cut Line= 3
 2295095.7676572485277.4678464262295376.40499748485253.040464528
 2295466.4004566485066.784039639
#Sta/Elev= 30
       0 2629.68     4.4 2628.61    20.5 2625.52    28.5 2623.66    32.5 2622.95
    40.6 2622.09    80.7 2618.83   108.8 2617.61   116.8 2617.53   132.9 2617.74
     161 2617.51   173.1 2617.22     189 2617.28   200.1 2616.05   206.8 2615.61
   221.2 2614.97   225.3    2615  227.46  2615.6   229.6 2616.19   233.2 2616.86
   237.3 2616.75   245.3  2617.7   293.4 2618.52   317.1 2619.12   356.3 2619.27
   392.6 2620.44     437 2621.09   446.7 2621.48   462.4 2621.51   488.6 2622.01
#Mann= 4 ,-1,0
       0     .06       0      40     .05       0   206.8    .045       0
  227.46     .05       0
#XS Ineff= 2 , 0
          129.71 2619.31
Permanent Ineff=
       F       F
Bank Sta=206.8,227.46
XS Rating Curve= 0 ,0
Exp/Cntr(USF)=0,0
Exp/Cntr=0.3,0.1

Type RM Length L Ch R = 1 ,366     ,224.5,223.9,225.6
XS GIS Cut Line= 2
2295269.32179295485529.8619400512295466.97004811485128.869514602
#Sta/Elev= 30
       0  2650.9     6.5 2649.28    20.6 2644.15    40.9 2634.64    53.4 2628.41
    63.2 2624.28    72.1 2620.79    77.3 2618.43    85.5 2615.65      90 2613.62
    92.3 2612.94    94.4 2612.44    98.2 2612.35   104.82612.947   107.8 2613.47
   119.1 2614.77   125.6 2615.28   135.9 2615.57   183.6 2616.04   202.8 2617.45
   214.8 2617.22     246 2617.86   267.8 2617.87   290.6 2618.39   340.2 2618.73
   353.1 2619.07   375.4 2619.26   386.4 2619.69   435.8 2620.73   447.1 2621.16
#Mann= 3 ,-1,0
       0     .05       0    92.3    .045       0   104.8     .05       0
Bank Sta=92.3,104.8
XS Rating Curve= 0 ,0
Exp/Cntr(USF)=0,0
Exp/Cntr=0.3,0.1

Type RM Length L Ch R = 1 ,142     ,116.7,116.7,116.7
XS GIS Cut Line= 4
2295409.06157758 485615.363955012295489.75370865485545.240910913
2295547.09258767485434.8034452552295555.00358091485130.578289142
#Sta/Elev= 30
       0 2627.26     4.1 2626.86    15.5 2626.52    49.1 2623.58    76.5 2621.66
    94.5 2619.74   106.9 2618.94     116 2617.64   120.5 2616.26   129.5 2612.75
   135.4  2611.2   147.5 2609.87   161.1  2609.4   168.1 2609.17   179.1 2609.41
   197.1 2612.34   201.6 2612.63   209.6 2612.38   218.5  2612.9   228.7 2615.02
     233 2615.44     245 2615.21   261.3 2615.37     297 2616.06     325 2617.02
     365 2617.27     405 2618.28   420.9 2619.03     485 2620.23   535.7 2620.63
#Mann= 3 ,-1,0
       0     .05       0   161.1    .045       0   179.1     .05       0
#XS Ineff= 2 , 0
                           201.8         2613.51
Permanent Ineff=
       F       F
Bank Sta=161.1,179.1
XS Rating Curve= 0 ,0
Exp/Cntr(USF)=0,0
Exp/Cntr=0.3,0.1

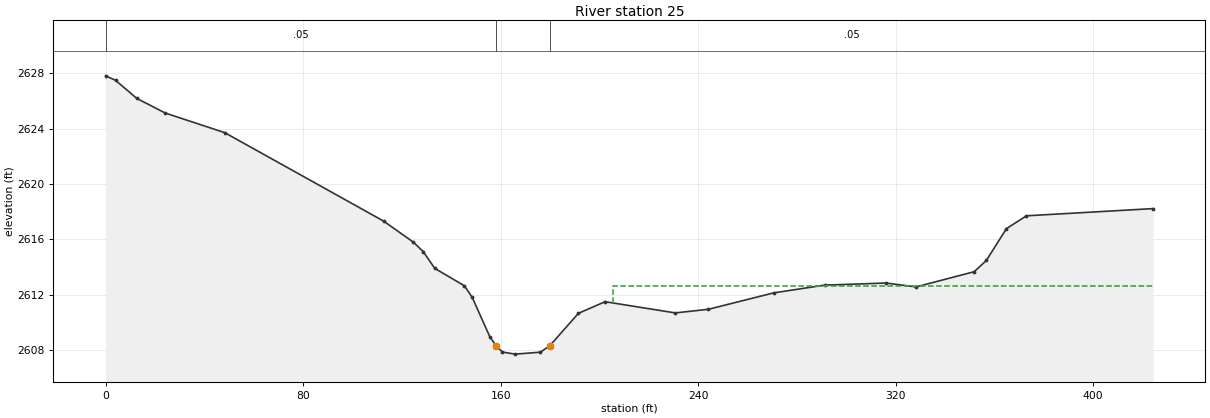
Type RM Length L Ch R = 1 ,25      ,,,
XS GIS Cut Line= 4
2295412.19752149485622.9233973092295553.96024421485608.920628948
2295595.60191113485575.4710300982295636.21786372485350.715613042
#Sta/Elev= 30
       0 2627.81       4 2627.48   12.55 2626.18   24.09 2625.12   48.21  2623.7
  112.52 2617.31  124.58 2615.79   128.6  2615.1  133.27 2613.89  145.29 2612.63
  148.43  2611.8  155.55 2608.96  158.07  2608.3  160.69 2607.84  165.82 2607.69
  176.08 2607.83  179.94 2608.31  191.47 2610.64  202.26 2611.48  230.71 2610.67
  244.07 2610.93  270.63 2612.12  291.28 2612.68  316.07 2612.83  328.27 2612.55
   351.8 2613.65  356.72 2614.46  364.85 2616.76  372.98 2617.69  424.26 2618.21
#Mann= 3 ,-1,0
       0     .05       0  158.07    .045       0  179.94     .05       0
#XS Ineff= 2 , 0
                          205.35         2612.63
Permanent Ineff=
       F       F
Bank Sta=158.07,179.94
XS Rating Curve= 0 ,0
Exp/Cntr(USF)=0,0
Exp/Cntr=0.3,0.1
LCMann Table=0

Chan Stop Cuts=-1
Use User Specified Reach Order=0
Composite Channel Slope=5